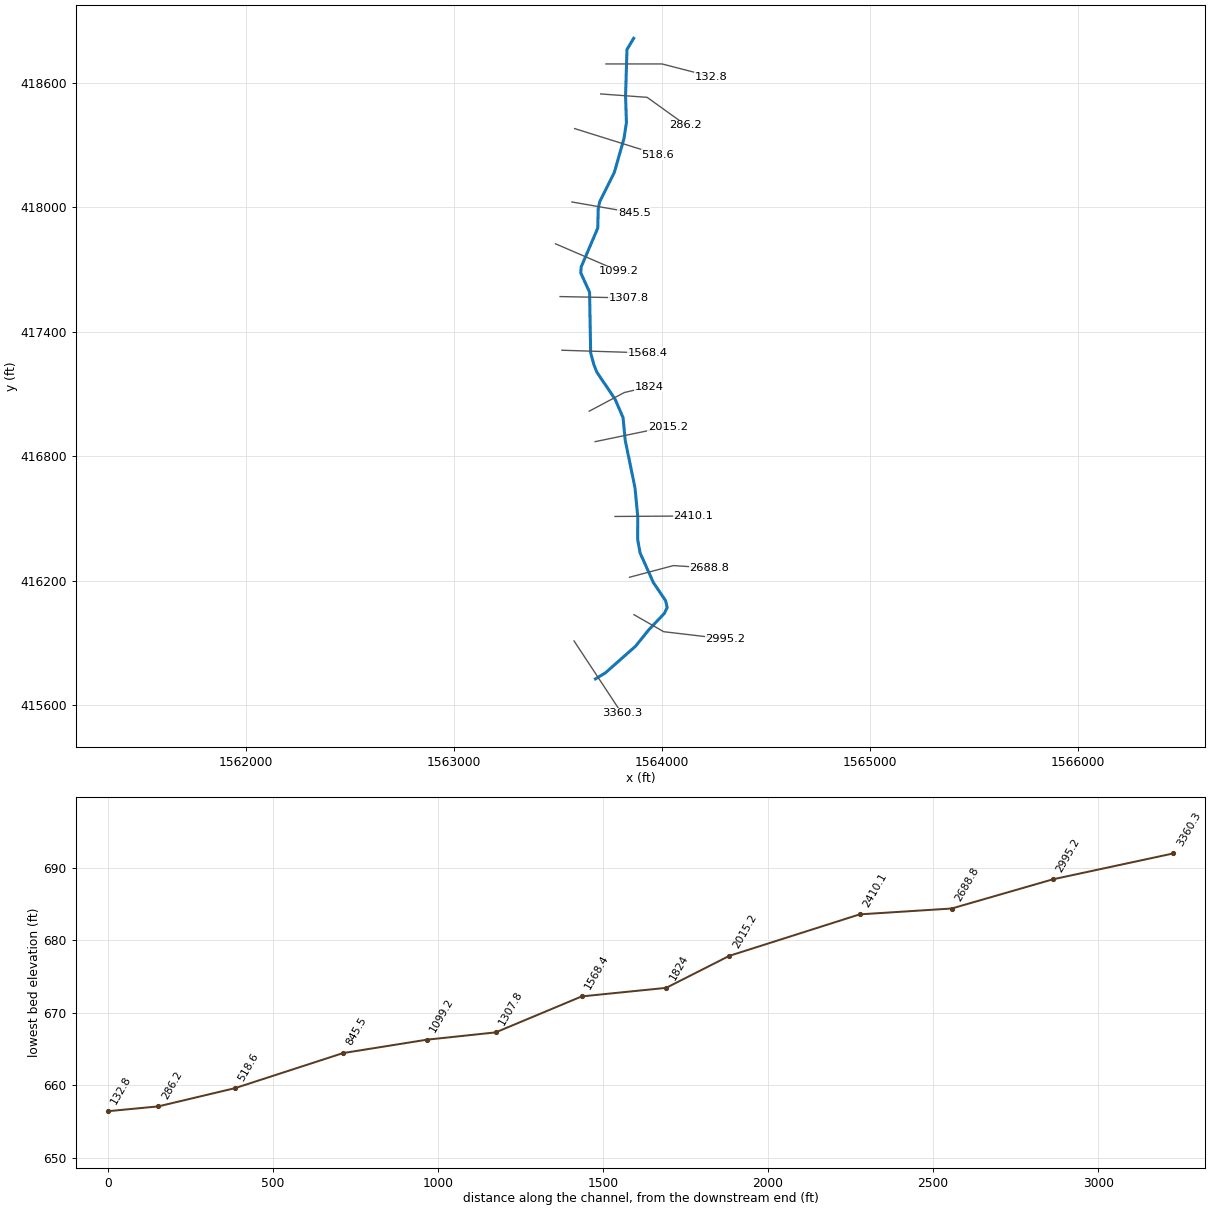
--- LFLYNNCR.prj (project) ---

Proj Title=LFLYNNCR
Current Plan=p01
Default Exp/Contr=0,0
English Units
Geom File=g01
Flow File=f01
Plan File=p01
BEGIN DESCRIPTION:
END DESCRIPTION:
DSS Export Rating Curves= 0
DSS Export Rating Curve Sorted= 0
DSS Export Volume Flow Curves= 0
DXF OffsetX= 0
DXF OffsetY= 0
DXF ScaleX= 0
DXF ScaleY= 0

--- LFLYNNCR.p01 (plan) ---

Plan Title=Floodplain
Program Version=4.00
Geom File=g01
Flow File=f01
K Sum by GR=0
Std Step Tol=0.01
Critical Tol=0.01
Num of Std Step Trials=20
Max Error Tol=0.3
Flow Tol Ratio=0.001
Split Flow NTrial=30
Split Flow Tol=0.02
Split Flow Ratio=0.02
Log Output Level=0
Friction Slope Method=1
Unsteady Friction Slope Method=2
Unsteady Bridges Friction Slope Method=1
Global Log Level=0
CheckData=False
Run HTab=0
Run UNet=0
Run PostProcess=0
UNET Theta=0
UNET Theta Warmup=0
UNET ZTol=0
UNET ZSATol=0
UNET MxIter=0
UNET MaxInSteps=0
UNET DtIC=0
UNET DtMin=0
UNET MaxCRTS=0
UNET WFStab=0
UNET SFStab=0
UNET WFX=0
UNET SFX=0
UNET DSS MLevel=0
UNET DZMax Abort=0
UNET Convert EG Bridges=0
UNET Use Existing IB Tables=0
UNET Froude Limit=0
UNET Froude Power=0
Write IC File=0
Echo Input=False
Echo Output=False
Write Detailed=0

--- LFLYNNCR.f01 (steady flow) ---

Flow Title=NFF Regression Equation
Program Version=4.00
Number of Profiles= 1
Profile Names=P100yr
River Rch & RM=LFLYNNCR,Main            ,3360.3
370.8797
River Rch & RM=LFLYNNCR,Main            ,2995.2
373.5043
River Rch & RM=LFLYNNCR,Main            ,2688.8
412.1778
River Rch & RM=LFLYNNCR,Main            ,286.2
454.6032
Boundary for River Rch & Prof#=LFLYNNCR,Main            , 1
Up Type= 0
Dn Type= 3
Dn Slope=0.011
DSS Import GetInterval= 0
DSS Import GetPeak= 0
DSS Import FillOption= 0

--- LFLYNNCR.g01 (geometry) ---

Geom Title=Geometry
Program Version=4.00

River Reach=LFLYNNCR        ,Main
Reach XY= 30
     1563680.855      415725.929     1563729.238      415755.598
     1563873.723      415883.565     1563936.145      415961.313
     1564012.302      416041.782     1564025.707      416070.395
     1564018.339      416102.803     1563959.528      416189.778
     1563895.357      416333.489      1563883.67      416399.052
       1563884.3      416507.225     1563870.903      416647.541
     1563823.971      416875.303     1563813.444      416985.416
     1563774.734      417075.017      1563687.58      417203.754
     1563673.096      417240.605     1563657.799      417297.004
     1563652.553      417589.703     1563610.225      417682.228
     1563611.963      417710.956     1563691.912      417898.512
     1563694.151      417991.948     1563701.619       418026.45
      1563771.59       418166.66      1563817.89      418329.391
      1563829.82      418406.928     1563825.555      418535.689
      1563832.47      418759.276     1563864.431      418812.882

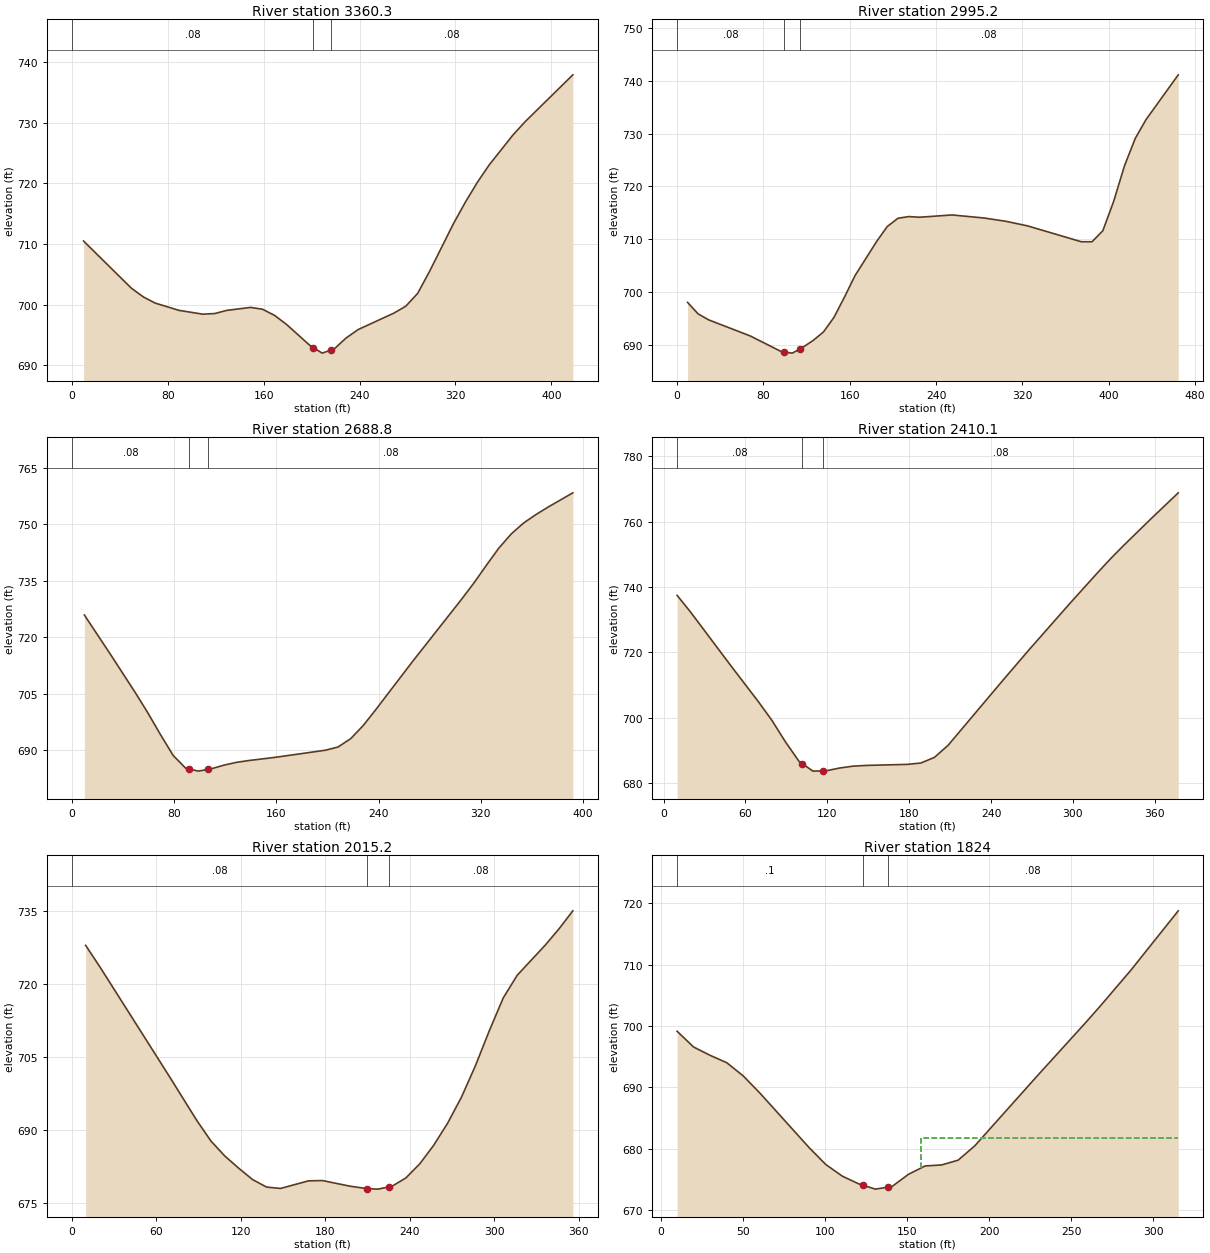
Type RM Length L Ch R = 1 ,3360.3  ,354.5,365.1,375.7
XS GIS Cut Line= 2
     1563577.857      415908.916     1563807.476      415559.803
#Sta/Elev= 30
     9.9   710.5    49.7  702.74    59.7  701.29    69.6  700.27    89.5  699.07
   109.4  698.44   119.4  698.55   129.3  699.07   149.2  699.56   159.2  699.25
   169.1  698.25   179.1  696.76     199  693.22   201.4  692.93   208.9  692.02
   216.4  692.54   218.9  692.71   228.8  694.51   238.8   695.9   268.6  698.61
   278.6  699.76   288.5  701.87   298.5  705.53   318.4  713.39   328.3  716.92
   338.3  720.19   348.2  723.07   368.1  728.02   378.1  730.18   417.9  737.91
#Mann= 3 , 0 , 0
       0     .08       0   201.4    .045       0   216.4     .08       0
Bank Sta=201.4,216.4
XS Rating Curve= 0 ,0
Exp/Cntr=0.3,0.1

Type RM Length L Ch R = 1 ,2995.2  ,288.2,306.4,324.6
XS GIS Cut Line= 3
     1563866.052       416035.44     1564008.977      415953.434
     1564306.544      415918.288
#Sta/Elev= 30
     9.7  698.05    19.4  695.88    29.1  694.75    67.9  691.68    96.9  688.69
    99.1  688.64   106.6  688.44   114.1  689.22     126  690.83   135.7  692.47
   145.4  695.23   155.1  699.06   164.8   703.1   184.8  709.56   194.7  712.41
   204.7  713.99   214.7   714.3   224.7  714.18   254.7  714.61   284.6  714.03
   304.6  713.41   324.6  712.55   374.5  709.54   384.5  709.53   394.5  711.62
   404.5  717.16   414.5  723.87   424.5  729.09   434.5  732.66   464.4  741.15
#Mann= 3 , 0 , 0
       0     .08       0    99.1    .045       0   114.1     .08       0
Bank Sta=99.1,114.1
XS Rating Curve= 0 ,0
Exp/Cntr=0.3,0.1

Type RM Length L Ch R = 1 ,2688.8  ,284.4,278.7,273.1
XS GIS Cut Line= 3
     1563844.964      416215.855     1564055.838      416272.088
     1564229.223      416260.373
#Sta/Elev= 30
     9.9  725.88    29.8  715.69    49.6  705.33    59.5  699.92    69.4  694.13
    79.4  688.56    89.3  685.14    91.7  684.96    99.2  684.41   106.7  684.87
   109.1  685.02     119  685.99     129  686.75   138.9  687.24   158.7  688.05
   198.4  689.96   208.3  690.81   218.2  693.03   227.9  696.47   237.6  700.63
   266.5  713.48   305.1  730.12   314.8  734.47   324.4   739.1   334.1  743.64
   343.8  747.41   353.4  750.29   363.1  752.55   372.7  754.55     392  758.33
#Mann= 3 , 0 , 0
       0     .08       0    91.7    .045       0   106.7     .08       0
Bank Sta=91.7,106.7
XS Rating Curve= 0 ,0
Exp/Cntr=0.3,0.1

Type RM Length L Ch R = 1 ,2410.1  ,390.4,394.8,399.3
XS GIS Cut Line= 2
     1563774.673      416508.735     1564151.903      416511.078
#Sta/Elev= 26
     9.9  737.42    19.9  732.23    49.6  715.71    69.5  704.84    79.4  699.13
    89.3  692.55    99.3  686.57   101.7  685.87  109.43   683.6   116.7  683.69
   119.1  683.69   129.1  684.56     139  685.13   148.9  685.35   178.7  685.67
   188.6  686.09   198.5  687.81   208.5  691.51   248.2  711.18     268  720.84
   297.8  734.98   317.7  744.19   327.6  748.66   337.5  752.85   357.4  760.95
   377.2  768.83
#Mann= 3 , 0 , 0
     9.9     .08       0   101.7    .045       0   116.7     .08       0
Bank Sta=101.7,116.7
XS Rating Curve= 0 ,0
Exp/Cntr=0.3,0.1

Type RM Length L Ch R = 1 ,2015.2  ,184.7,191.2,197.6
XS GIS Cut Line= 2
     1563679.443      416869.273     1564027.928        416941.6
#Sta/Elev= 30
     9.9  727.87    19.8  723.54    29.7  719.05    69.2  701.05      89  691.88
    98.9  687.73   108.8  684.64   118.6  682.16   128.5  679.82   138.4  678.29
   148.3  678.01   168.1  679.56     178  679.63   197.7  678.47     210  677.96
   217.5  677.87     225  678.31   227.4  678.45   237.3  680.16   247.2  683.06
     257  686.83   266.9  691.36   276.8  696.73   286.7  703.17   296.6  710.37
   306.5   717.1   316.4  721.74   336.1  727.85     346  731.23   355.9  734.95
#Mann= 3 , 0 , 0
       0     .08       0     210    .045       0     225     .08       0
Bank Sta=210,225
XS Rating Curve= 0 ,0
Exp/Cntr=0.3,0.1

Type RM Length L Ch R = 1 ,1824    ,267.4,255.7,243.9
XS GIS Cut Line= 3
     1563650.884      417016.146     1563819.647      417106.007
     1563940.192        417134.5
#Sta/Elev= 24
    10.1  699.15    20.1  696.59    30.2  695.23    40.3  694.03    50.3  691.89
    60.4  689.11    90.6  680.16   100.6  677.45   110.7  675.55   120.8  674.29
   123.3  674.08   130.8  673.45   138.3  673.77   140.9  673.88   150.9  675.86
     161  677.22   171.1  677.39   181.1  678.16   191.2  680.48   229.3  691.89
   257.9  700.31   267.4  703.18   286.5  709.17   315.1  718.76
#Mann= 3 , 0 , 0
    10.1      .1       0   123.3    .045       0   138.3     .08       0
#XS Ineff= 2 , 0
                          158.39           681.7
Permanent Ineff=
       F       F
Bank Sta=123.3,138.3
XS Rating Curve= 0 ,0
Exp/Cntr=0.3,0.1

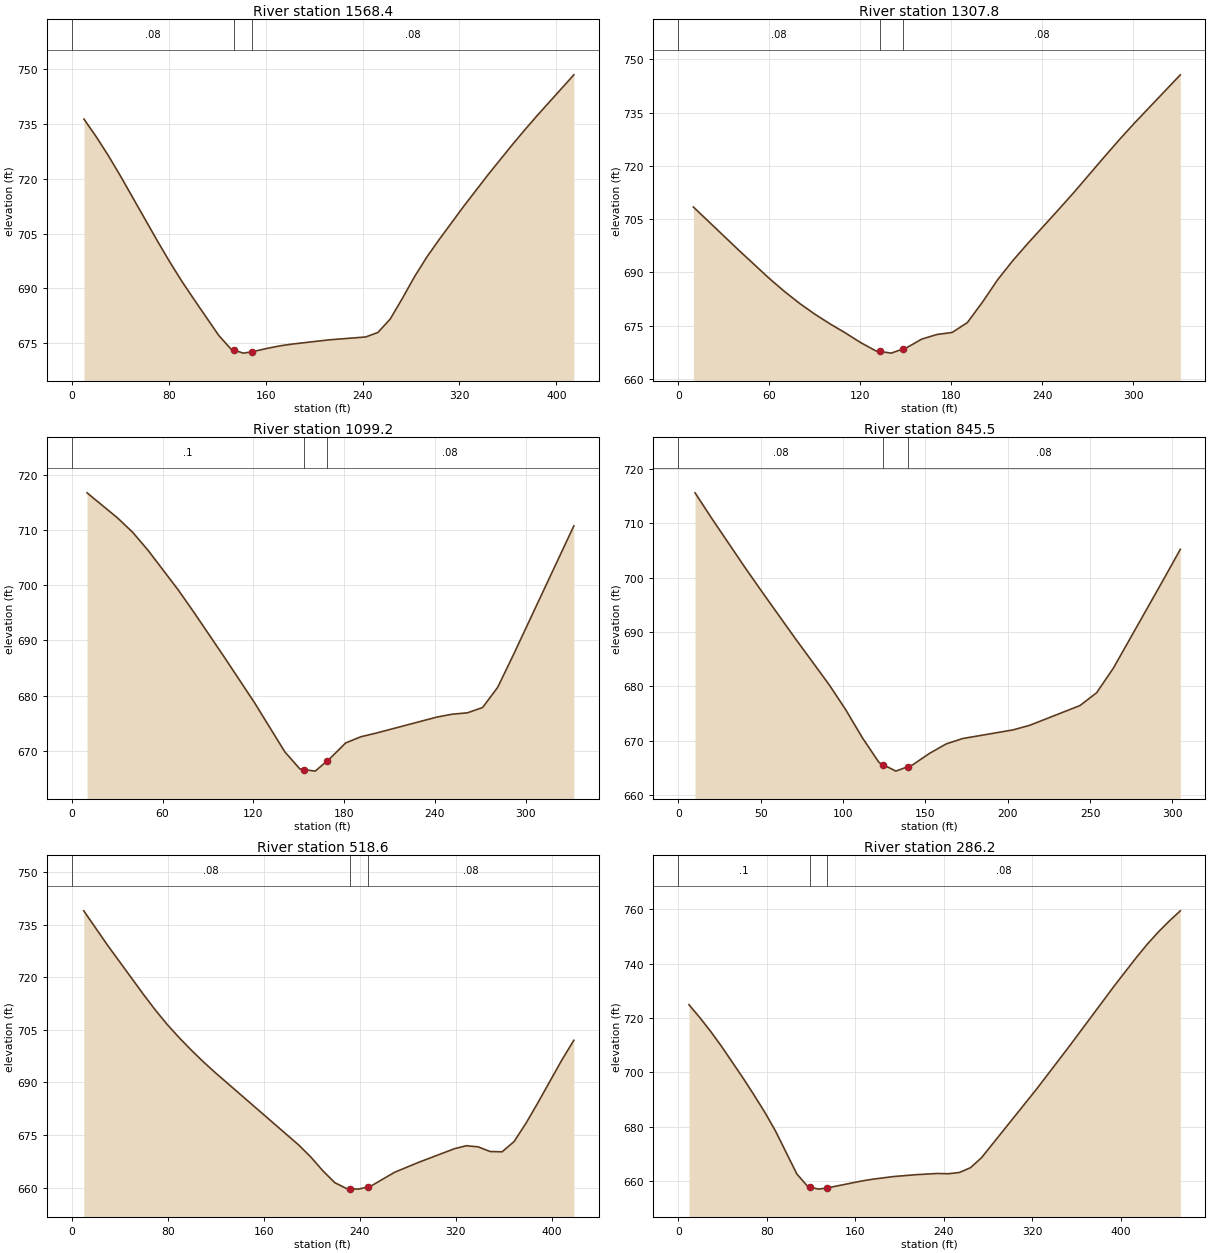
Type RM Length L Ch R = 1 ,1568.4  ,260.3,260.6,260.8
XS GIS Cut Line= 2
     1563519.447       417309.81     1563933.683       417296.66
#Sta/Elev= 30
    10.1  736.29    20.2  731.48    30.3  726.26    40.4  720.62    70.8   702.9
    80.9  697.21      91  691.86   101.1  686.88   121.3  677.12   131.4  673.39
     134   673.1   141.5  672.27     149  672.64   161.7   673.6   171.8  674.26
     182  674.75   212.3   675.9   242.6  676.69   252.7  677.93   262.8  681.58
   272.9  687.26     283  693.24   293.1  698.58   303.3  703.37   323.5  712.45
   343.7  721.13   363.9  729.41     374   733.4   384.1  737.26   414.4  748.42
#Mann= 3 , 0 , 0
       0     .08       0     134    .045       0     149     .08       0
Bank Sta=134,149
XS Rating Curve= 0 ,0
Exp/Cntr=0.3,0.1

Type RM Length L Ch R = 1 ,1307.8  ,217.4,208.6,199.8
XS GIS Cut Line= 2
      1563510.68      417568.434     1563841.631      417561.859
#Sta/Elev= 28
      10  708.43    40.1   696.2    60.2  688.26    70.2   684.6    80.2  681.24
    90.3   678.2   100.3  675.48   110.3  672.96   120.4  670.23   130.4  667.92
   132.9  667.77   140.4   667.3   147.9  668.42   150.5   668.8   160.5  671.24
   170.5  672.54   180.6  673.12   190.6   675.9   200.6  681.67   210.6  687.98
   220.7  693.41   230.7  698.29   250.8  707.73   260.8  712.51   280.9  722.53
   290.9  727.43   300.9  732.11     331  745.64
#Mann= 3 , 0 , 0
       0     .08       0   132.9    .045       0   147.9     .08       0
Bank Sta=132.9,147.9
XS Rating Curve= 0 ,0
Exp/Cntr=0.3,0.1

Type RM Length L Ch R = 1 ,1099.2  ,248.3,253.7,259
XS GIS Cut Line= 2
     1563488.762      417822.675     1563793.413      417691.171
#Sta/Elev= 24
    10.1  716.75    30.2  712.21    40.2  709.61    50.3  706.37    70.4  699.13
    80.4  695.22   100.6  687.04   120.7  678.73   140.8  669.79   150.8  666.67
   153.4  666.57   160.9  666.29   168.4  668.06   170.9  668.65     181   671.4
     191  672.52   201.1  673.18   241.3  676.09   251.4  676.61   261.4  676.86
   271.5  677.82   281.5   681.5   291.6  687.23   331.8  710.76
#Mann= 3 , 0 , 0
       0      .1       0   153.4    .045       0   168.4     .08       0
Bank Sta=153.4,168.4
XS Rating Curve= 0 ,0
Exp/Cntr=0.3,0.1

Type RM Length L Ch R = 1 ,845.5   ,329.9,326.9,324
XS GIS Cut Line= 2
     1563567.665      418024.314     1563867.931      417971.712
#Sta/Elev= 23
    10.2  715.57    20.3   710.9    40.6  701.82    50.8  697.41    71.1  688.79
    91.5  680.37   101.6  675.76   111.8  670.57   121.9  666.02   124.6   665.6
   132.1  664.44   139.6  665.28   142.3  665.59   152.4  667.67   162.6  669.43
   172.7  670.43   203.2  672.01   213.4  672.86   243.9  676.49     254  678.84
   264.2  683.38   294.7   699.7   304.8  705.19
#Mann= 3 , 0 , 0
       0     .08       0   124.6    .045       0   139.6     .08       0
Bank Sta=124.6,139.6
XS Rating Curve= 0 ,0
Exp/Cntr=0.3,0.1

Type RM Length L Ch R = 1 ,518.6   ,227.1,232.4,237.6
XS GIS Cut Line= 2
     1563580.678       418377.98     1563980.112      418252.785
#Sta/Elev= 30
      10  738.91    29.9  729.08    59.8  715.08    69.8  710.59    79.7  706.47
    89.7  702.71    99.7   699.2   109.6  695.92   119.6  692.81   189.4  672.12
   199.3  668.75   209.3  664.84   219.3  661.44   229.2  659.75   231.7  659.71
   239.2   659.6   246.7  660.22   249.2  660.43   269.1  664.39     289  667.21
   318.9   671.1   328.9  671.97   338.9  671.64   348.8  670.32   358.8  670.24
   368.8  673.16   378.7  678.38   388.7  684.26   408.6  696.39   418.6  702.02
#Mann= 3 , 0 , 0
       0     .08       0   231.7    .045       0   246.7     .08       0
Bank Sta=231.7,246.7
XS Rating Curve= 0 ,0
Exp/Cntr=0.3,0.1

Type RM Length L Ch R = 1 ,286.2   ,151.8,153.5,155.1
XS GIS Cut Line= 3
     1563705.873      418544.908     1563929.437      418528.513
      1564115.74      418394.375
#Sta/Elev= 30
     9.7  724.91    19.5  720.17    29.2  715.13      39  709.66    58.5  697.98
    68.2  691.88      78  685.51    87.7  678.61   107.2  662.65     117  658.08
   119.2  657.85   126.7  657.08   134.2  657.49   165.7  660.06   175.4  660.71
   194.9  661.72   214.4  662.38   234.1  662.83   244.1  662.74   254.1   663.2
   264.1  664.96   274.1  668.65     324  693.97   353.9  709.89   393.8   731.7
   413.8  742.17   423.8  747.14   433.8  751.62   443.8   755.7   453.7  759.43
#Mann= 3 , 0 , 0
       0      .1       0   119.2    .045       0   134.2     .08       0
Bank Sta=119.2,134.2
XS Rating Curve= 0 ,0
Exp/Cntr=0.3,0.1

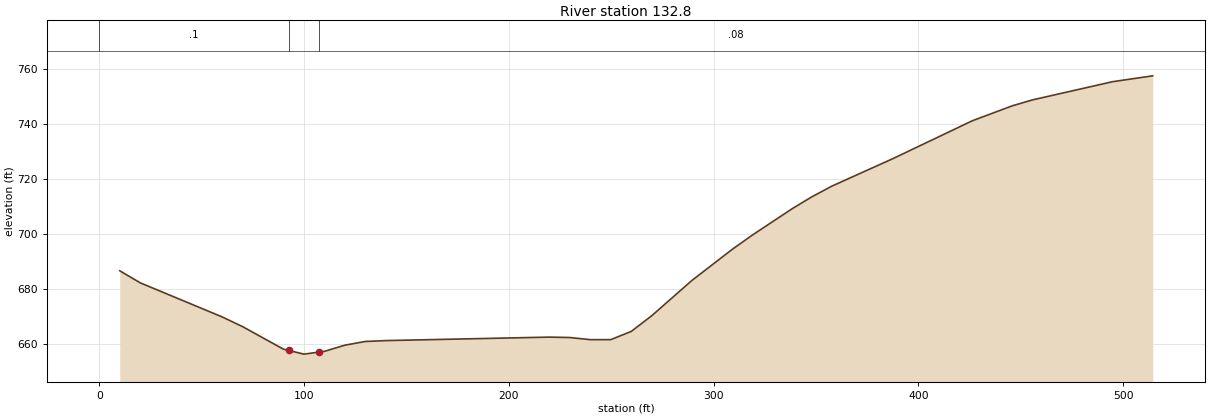
Type RM Length L Ch R = 1 ,132.8   ,147.7,132.8,117.8
XS GIS Cut Line= 3
     1563731.211      418689.479     1564000.978      418689.479
     1564237.955      418628.372
#Sta/Elev= 30
      10  686.71      20  682.33    59.9  669.97    69.9  666.44    89.9  658.22
    92.4  657.77    99.9  656.41   107.4  657.16   109.9  657.41   119.9  659.66
   129.9  661.01   139.9  661.33   219.8   662.6   229.8  662.45   239.8  661.67
   249.8  661.68   259.8  664.67   269.8  670.37   289.3  683.13   308.9  694.39
   318.7  699.58   338.3  709.25   348.1  713.66   357.9  717.55   387.2  727.37
   426.4  741.28     446  746.74   455.8  748.87   494.9  755.49   514.5  757.62
#Mann= 3 , 0 , 0
       0      .1       0    92.4    .045       0   107.4     .08       0
Bank Sta=92.4,107.4
XS Rating Curve= 0 ,0
Exp/Cntr=0.3,0.1

Chan Stop Cuts=-1
Use User Specified Reach Order=0